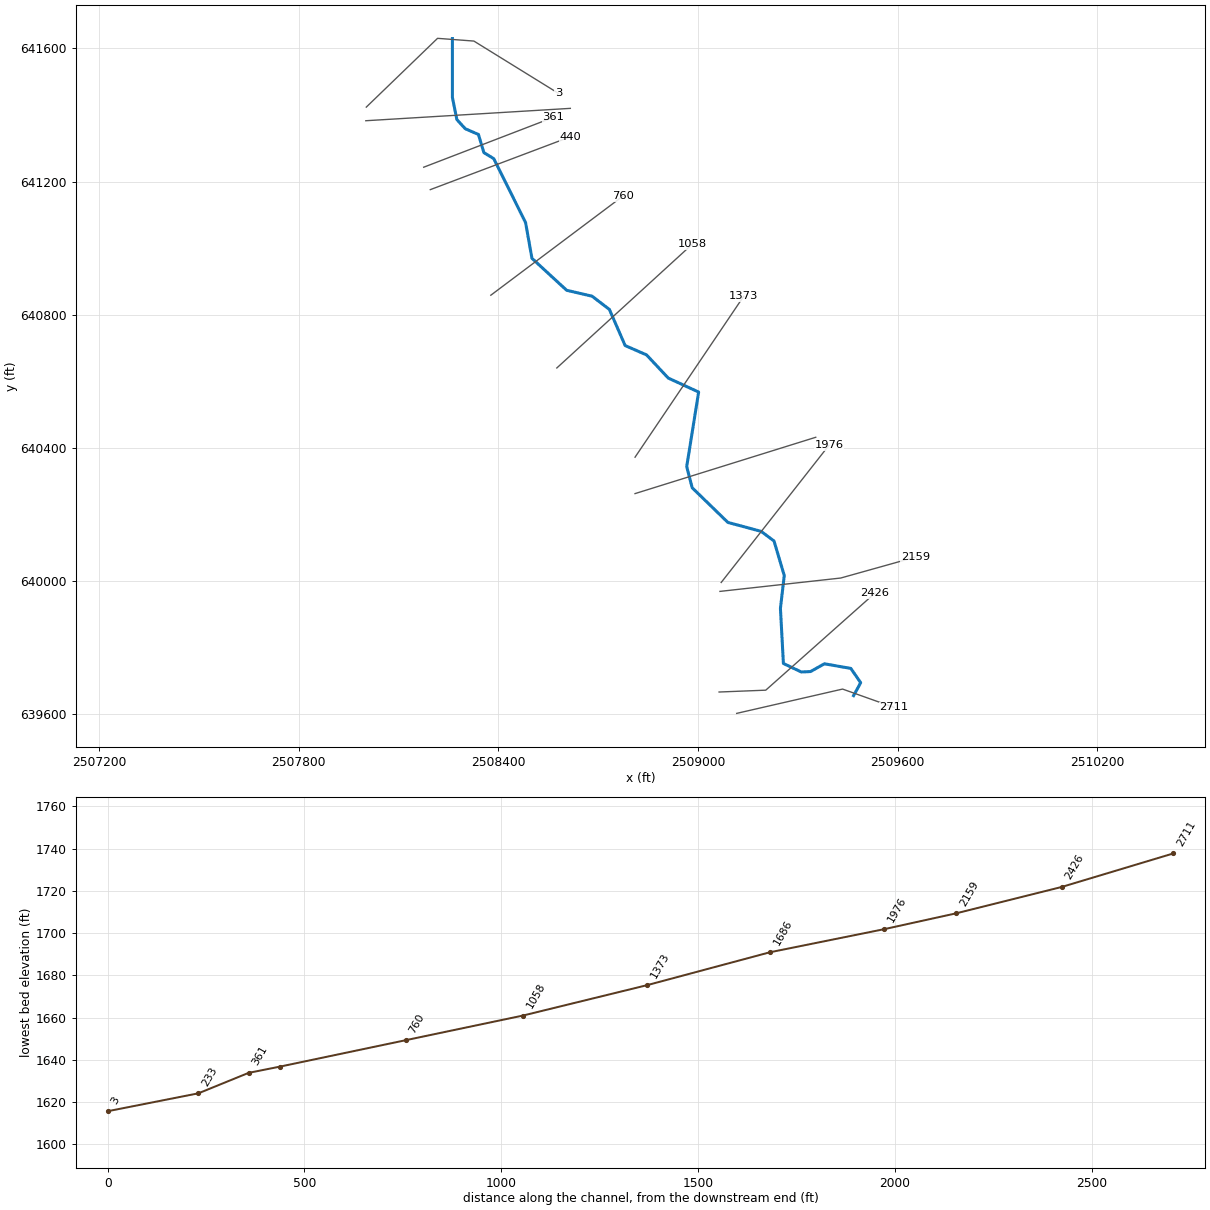
--- LITTLECMRN.prj (project) ---

Proj Title=LITTLECMRN
Current Plan=p01
Default Exp/Contr=0,0
English Units
Geom File=g01
Flow File=f01
Plan File=p01
BEGIN DESCRIPTION:
Stream Name: Little Camp Run
Flood Zone: Approximate
Pendleton County, West Virginia
HEC-RAS Version: 5.0.7
Hydrology Method:
Regression equation
END DESCRIPTION:
DSS Export Rating Curves= 0
DSS Export Rating Curve Sorted= 0
DSS Export Volume Flow Curves= 0
DXF OffsetX= 0
DXF OffsetY= 0
DXF ScaleX= 0
DXF ScaleY= 0

--- LITTLECMRN.p01 (plan) ---

Plan Title=Floodplain
Program Version=5.07
Short Identifier=Floodplain
Geom File=g01
Flow File=f01
Subcritical Flow
K Sum by GR= 0
Std Step Tol= 0.01
Critical Tol= 0.01
Num of Std Step Trials= 20
Max Error Tol= 0.3
Flow Tol Ratio= 0.001
Split Flow NTrial= 30
Split Flow Tol= 0.02
Split Flow Ratio= 0.02
Log Output Level= 0
Friction Slope Method= 1
Unsteady Friction Slope Method= 2
Unsteady Bridges Friction Slope Method= 1
Parabolic Critical Depth
Global Vel Dist= 0 , 0 , 0
Global Log Level= 0
CheckData=True
Encroach Param=-1 ,0,0, 0
Mapping Interval=1HOUR
Computation Time Step Use Courant=        0
Computation Time Step Use Time Series=    0
Computation Time Step Count To Double=0
Computation Time Step Max Doubling=0
Computation Time Step Max Halving=0
Computation Time Step Residence Courant=0
Run HTab= 0
Run UNet= 0
Run Sediment= 0
Run PostProcess= 0
Run WQNet= 0
Run RASMapper= 0
UNET Theta= 0
UNET Theta Warmup= 0
UNET ZTol= 0
UNET ZSATol= 0
UNET MxIter= 0
UNET Max Iter WO Improvement= 0
UNET MaxInSteps= 0
UNET DtIC= 0
UNET DtMin= 0
UNET MaxCRTS= 0
UNET WFStab= 0
UNET SFStab= 0
UNET WFX= 1
UNET SFX= 1
UNET 1D Methodology=Finite Difference
UNET DSS MLevel= 1
UNET Pardiso=0
UNET DZMax Abort= 0
UNET Use Existing IB Tables= 0
UNET Froude Reduction=False
UNET Froude Limit= 0
UNET Froude Power= 0
UNET D1 Cores= 0
UNET D2 Coriolis=0
UNET D2 Cores= 0
UNET D2 Theta= 1
UNET D2 Theta Warmup= 1
UNET D2 Z Tol= 0.01
UNET D2 Volume Tol= 0.01
UNET D2 Max Iterations= 20
UNET D2 Equation= 0
UNET D2 RampUpFraction=0.1
UNET D2 TimeSlices= 1
UNET D2 BCVolumeCheck=0
UNET D1D2 MaxIter= 0
UNET D1D2 ZTol=0.01
UNET D1D2 QTol=0.1
UNET D1D2 MinQTol=1
Write IC File= 0
Write IC File at Fixed DateTime=0
Write IC File at Sim End=0
Echo Input=False
Echo Parameters=False
Echo Output=False
Write Detailed= 0
HDF Write Warmup=0
HDF Write Time Slices=0
HDF Flush=0
HDF Face Node Velocities=0
HDF Compression= 1
HDF Chunk Size= 1
HDF Spatial Parts= 1
HDF Use Max Rows=0
HDF Fixed Rows= 1
Calibration Method= 0
Calibration Iterations= 20
Calibration Max Change=0.05
Calibration Tolerance=0.2
Calibration Maximum=1.5
Calibration Minimum=0.5
Calibration Optimization Method= 1
WQ AD Non Conservative
WQ ULTIMATE=-1
WQ Max Comp Step=1HOUR
WQ Output Interval=15MIN
WQ Output Selected Increments= 0
WQ Output face flow=0
WQ Output face velocity=0
WQ Output face area=0
WQ Output face dispersion=0
WQ Output cell volume=0
WQ Output cell surface area=0
WQ Output cell continuity=0
WQ Output cumulative cell continuity=0
WQ Output face conc=0
WQ Output face dconc_dx=0
WQ Output face courant=0
WQ Output face peclet=0
WQ Output face adv mass=0
WQ Output face disp mass=0
WQ Output cell mass=0
WQ Output cell source sink temp=0
WQ Output nsm pathways=0
WQ Output nsm derived pathways=0
WQ Output MaxMinRange=-1
WQ Daily Max Min Mean=-1
WQ Daily Range=0
WQ Daily Time=0
WQ Create Restart=0
WQ Fixed Restart=0
WQ System Summary=0
WQ Write To DSS=0
WQ Use Fixed Temperature=0
Sorting and Armoring Iterations= 10
XS Update Threshold= 0.02
Bed Roughness Predictor= 0
Hydraulics Update Threshold= 0.02
Energy Slope Method= 1
Volume Change Method= 1
Sediment Retention Method= 0
XS Weighting Method= 0
Number of US Weighted Cross Sections= 1
Number of DS Weighted Cross Sections= 1
Upstream XS Weight=0
Main XS Weight=1
Downstream XS Weight=0
Number of DS XS's Weighted with US Boundary= 1
Upstream Boundary Weight= 1
Weight of XSs Associated with US Boundary= 0
Number of US XS's Weighted with DS Boundary= 1
Downstream Boundary Weight= 0.5
Weight of XSs Associated with DS Boundary= 0.5
Percentile Method= 0
Sediment Output Level= 3
Mass or Volume Output= 0
Output Increment Type= 1
Profile and TS Output Increment= 1
XS Output Flag= 0
XS Output Increment= 10
Write Gradation File= 0
Read Gradation Hotstart= 0
Write HDF5 File= 1
Write Binary Output= 1
Write DSS Sediment File= 0
SV Curve= 0
Specific Gage Flag= 0

--- LITTLECMRN.f01 (steady flow) ---

Flow Title=Flows
Program Version=5.07
Number of Profiles= 6
Profile Names=P100yr,P10yr,P25yr,P50yr,P500yr,P101yr
River Rch & RM=LITTLECMRN,Main            ,2711
     583     273     385     481     855     709
Boundary for River Rch & Prof#=LITTLECMRN,Main            , 1
Up Type= 0
Dn Type= 3
Dn Slope=0.04209
Boundary for River Rch & Prof#=LITTLECMRN,Main            , 2
Up Type= 0
Dn Type= 3
Dn Slope=0.04209
Boundary for River Rch & Prof#=LITTLECMRN,Main            , 3
Up Type= 0
Dn Type= 3
Dn Slope=0.04209
Boundary for River Rch & Prof#=LITTLECMRN,Main            , 4
Up Type= 0
Dn Type= 3
Dn Slope=0.04209
Boundary for River Rch & Prof#=LITTLECMRN,Main            , 5
Up Type= 0
Dn Type= 3
Dn Slope=0.04209
Boundary for River Rch & Prof#=LITTLECMRN,Main            , 6
Up Type= 0
Dn Type= 3
Dn Slope=0.04209
DSS Import GetInterval= 0
DSS Import GetPeak= 0
DSS Import FillOption= 0

--- LITTLECMRN.g01 (geometry) ---

Geom Title=Geometry
Program Version=5.07

River Reach=LITTLECMRN      ,Main
Reach XY= 30
     2509467.668      639655.107     2509488.955        639693.9
     2509459.335       639736.93      2509379.91      639750.845
     2509338.343      639727.485     2509310.486      639726.223
     2509256.705      639751.795     2509247.775      639917.347
     2509259.292      640016.143     2509228.458       640119.89
     2509189.837      640148.798     2509089.827      640175.687
     2508982.691      640279.725     2508966.087      640343.193
     2509001.948      640567.459     2508910.536      640609.598
     2508845.462      640679.134     2508781.083      640707.198
     2508733.772      640815.767     2508681.728       640855.58
     2508605.323      640873.326     2508501.038      640969.359
     2508481.837      641076.879     2508386.267      641268.949
2508356.59555567641286.936363955     2508340.235      641341.568
     2508300.588      641358.876     2508275.354      641386.386
     2508261.918      641453.174      2508261.92      641629.841

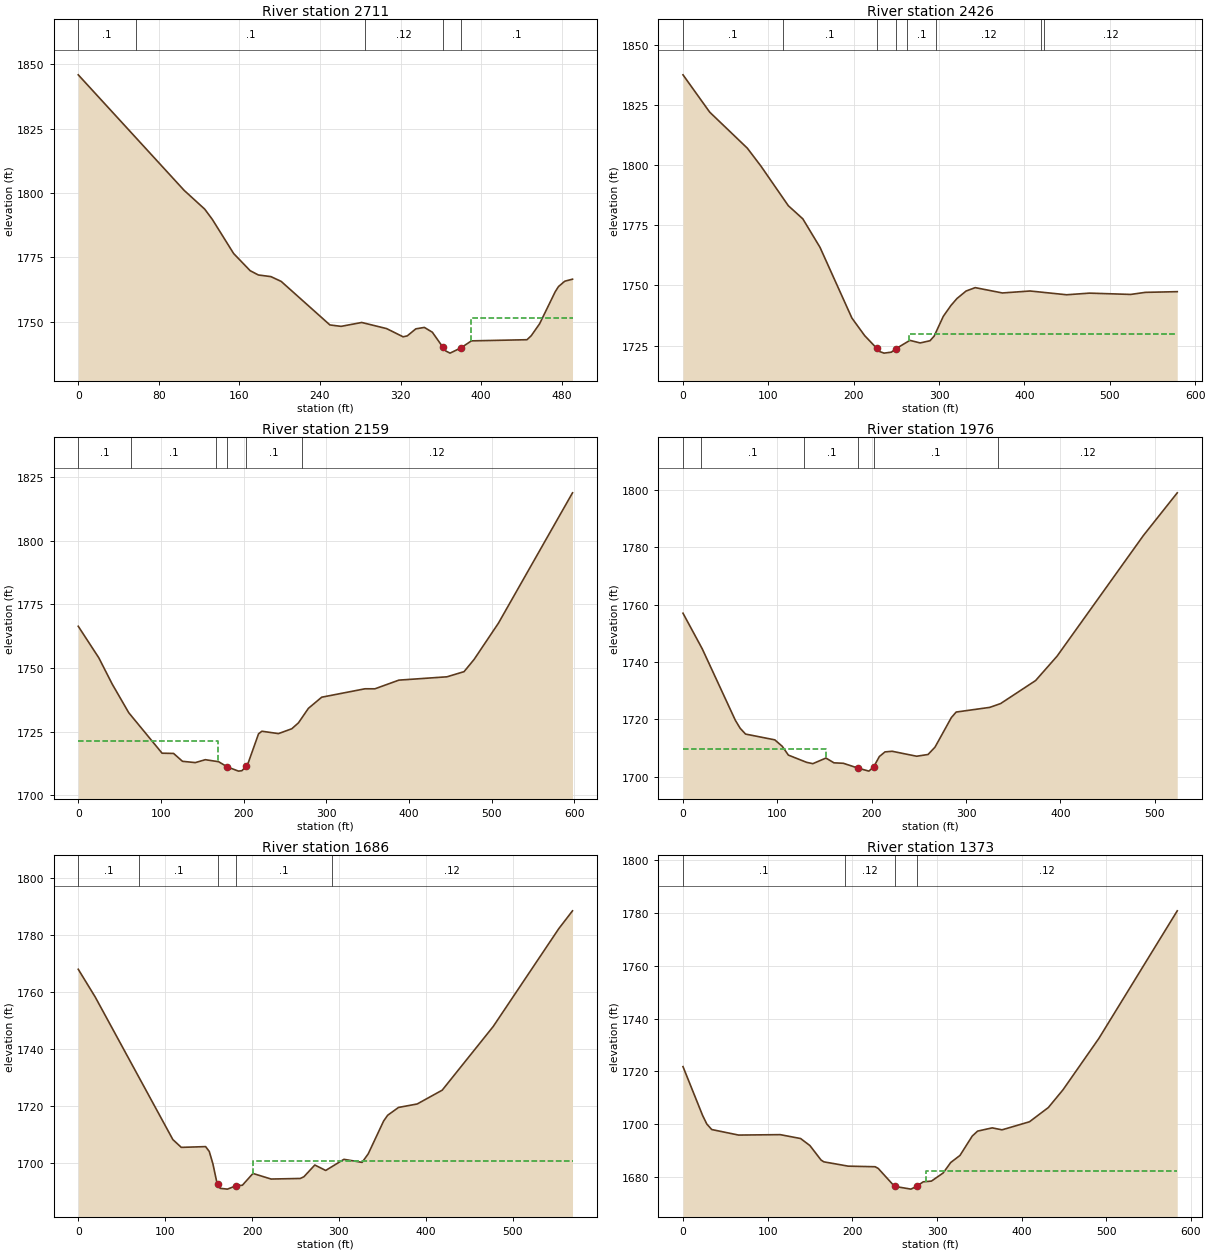
Type RM Length L Ch R = 1 ,2711    ,273.1,284.4,305.8
XS GIS Cut Line= 3
2509116.33869386639601.8080404332509434.46002886639674.851083077
2509589.34493415639619.686558195
#Sta/Elev= 30
       0 1845.89   105.1 1801.02   125.6  1793.7   133.1 1789.74   154.3 1776.46
   170.7 1769.79   178.9 1768.12   191.3 1767.49   201.5 1765.63   249.9 1748.71
     261 1748.16   281.5 1749.67   306.2 1747.29   322.6  1744.1   326.7 1744.46
   335.2 1747.19   343.7 1747.75   351.6 1745.89     362 1740.11   364.9 1738.61
   369.2 1737.76   379.8 1739.76   390.4 1742.52   445.6 1742.97   449.8 1744.52
   458.1 1749.15   473.7 1761.67   476.9 1763.63   483.1  1765.7   490.8 1766.49
#Mann= 5 ,-1 , 0
       0      .1       0   56.88      .1       0   284.8     .12       0
     362    .045       0   379.8      .1       0
#XS Ineff= 2 , 0
                           389.7         1751.37
Permanent Ineff=
       F       F
Bank Sta=362,379.8
XS Rating Curve= 0 ,0
Exp/Cntr=0.3,0.1

Type RM Length L Ch R = 1 ,2426    ,275,267.1,257
XS GIS Cut Line= 3
2509063.44298673639665.996182035 2509203.7367177639671.554277078
2509531.58875468639962.980295564
#Sta/Elev= 30
       0 1837.59    31.3 1822.07    75.4 1807.08    91.4 1799.59   123.4 1783.16
   140.4 1777.69   160.5 1765.87   197.9 1736.44   212.9 1729.11   227.1 1723.82
   229.9 1722.56   235.6 1721.85   244.1 1722.25   249.7 1723.73   265.8 1727.16
   277.9 1726.09   289.4    1727   294.3 1728.94     305 1737.16     314 1741.69
     321 1744.56   331.7 1747.68   342.4 1749.09   374.2 1746.87   406.7 1747.69
   449.5 1746.12   476.2  1746.8   524.6 1746.26   541.6 1747.12   579.1 1747.41
#Mann= 8 ,-1 , 0
       0      .1       0  117.53      .1       0   227.1    .045       0
   249.7      .1       0  262.18      .1       0  297.01     .12       0
  419.45      .1       0  423.49     .12       0
#XS Ineff= 2 , 0
                          265.37         1729.84
Permanent Ineff=
       F       F
Bank Sta=227.1,249.7
XS Rating Curve= 0 ,0
Exp/Cntr=0.3,0.1

Type RM Length L Ch R = 1 ,2159    ,170.2,183.7,193
XS GIS Cut Line= 3
2509065.99033254639968.4005171822509428.96569365640008.565030886
2509653.03620052640071.269556765
#Sta/Elev= 30
       0  1766.4    24.9 1753.98      41  1743.7    61.1 1732.39   101.4 1716.47
   115.3 1716.38   126.1 1713.28   141.6 1712.77   153.7 1713.92   169.8 1713.12
   180.5 1711.05   193.9 1709.42     198 1709.59   203.11711.288   205.9 1712.93
   218.1 1724.09   222.1 1725.11   242.2 1724.18   258.3 1726.08   266.4 1728.42
   278.4 1734.11   294.5  1738.5   346.9 1741.81   358.9  1741.8   387.8 1745.21
     446 1746.52   466.7 1748.55   478.9 1753.38   508.3 1767.63   597.9 1818.89
#Mann= 6 ,-1 , 0
       0      .1       0   64.08      .1       0  167.09      .1       0
   180.5    .045       0   203.1      .1       0  270.23     .12       0
#XS Ineff= 2 , 0
          169.57 1721.29
Permanent Ineff=
       F       F
Bank Sta=180.5,203.1
XS Rating Curve= 0 ,0
Exp/Cntr=0.3,0.1

Type RM Length L Ch R = 1 ,1976    ,297.1,290,278.5
XS GIS Cut Line= 2
2509069.76752922639995.2095937382509393.37578396640407.141265043
#Sta/Elev= 30
       0 1757.03    20.4  1744.6    55.5 1719.63    60.6 1716.85    66.3 1714.83
    97.3 1712.81   105.2 1710.55   111.7 1707.48   131.1 1704.95   137.6  1704.5
   151.5 1706.45     160 1704.79   169.9 1704.63   185.6 1702.94     197 1701.89
   202.11703.374   208.1 1706.99   214.1 1708.61   221.7 1708.82   247.6 1707.09
   259.7  1707.7   267.1 1710.28   284.4 1720.59   289.5 1722.52   325.1 1724.15
   336.6 1725.48   373.7 1733.52   396.4 1742.02   487.9 1784.16   523.8 1799.07
#Mann= 6 ,-1 , 0
       0      .1       0      19      .1       0  128.73      .1       0
   185.6    .045       0   202.1      .1       0  333.95     .12       0
#XS Ineff= 2 , 0
          151.48 1709.57
Permanent Ineff=
       F       F
Bank Sta=185.6,202.1
XS Rating Curve= 0 ,0
Exp/Cntr=0.3,0.1

Type RM Length L Ch R = 1 ,1686    ,296.2,312.3,321.9
XS GIS Cut Line= 2
2508810.80260939640262.2831987822509353.88639757640431.568663478
#Sta/Elev= 30
       0 1768.12    19.6 1758.35   108.9 1708.36   118.6 1705.62   146.6 1705.89
   150.8 1704.19     155 1699.83   159.2  1693.8   160.81692.703   163.3 1691.25
   171.7 1690.97   181.6 1692.14   188.9 1692.33   201.1 1696.47     222 1694.51
   255.5 1694.71   259.7  1695.3   272.3 1699.44   284.8 1697.52   305.8 1701.43
   326.7 1700.36   333.8 1703.37   351.5 1714.88   356.1 1716.88   368.6 1719.63
   390.1 1720.85   418.9 1725.69   477.6 1748.03   553.1 1782.37   568.9 1788.63
#Mann= 5 ,-1 , 0
       0      .1       0    70.1      .1       0   160.8    .045       0
   181.6      .1       0  292.09     .12       0
#XS Ineff= 2 , 0
                          201.33         1700.69
Permanent Ineff=
       F       F
Bank Sta=160.8,181.6
XS Rating Curve= 0 ,0
Exp/Cntr=0.3,0.1

Type RM Length L Ch R = 1 ,1373    ,317.9,315,310.7
XS GIS Cut Line= 2
2508810.87337473640371.7342111812509137.46231927640855.576696608
#Sta/Elev= 30
       0 1721.78    23.1 1703.34    28.1 1700.06    33.9 1697.96    65.6 1695.86
   114.8 1696.02   138.9 1694.55   149.9 1691.88   163.1 1686.39   166.4 1685.72
   195.2 1684.09   226.9 1683.87   230.6 1683.22   249.8 1676.44   269.2 1675.39
   275.9 1676.46   283.7 1678.15   293.4 1678.43   307.2  1681.5   316.2 1685.48
   327.1 1688.15   341.6 1695.49   347.9 1697.36   365.2 1698.59   376.7 1697.84
   409.2  1700.9   431.5  1706.3   448.8 1713.02   491.2  1732.5   583.7 1780.78
#Mann= 4 ,-1 , 0
       0      .1       0  191.06     .12       0   249.8    .045       0
   275.9     .12       0
#XS Ineff= 2 , 0
                          287.29         1682.11
Permanent Ineff=
       F       F
Bank Sta=249.8,275.9
XS Rating Curve= 0 ,0
Exp/Cntr=0.3,0.1

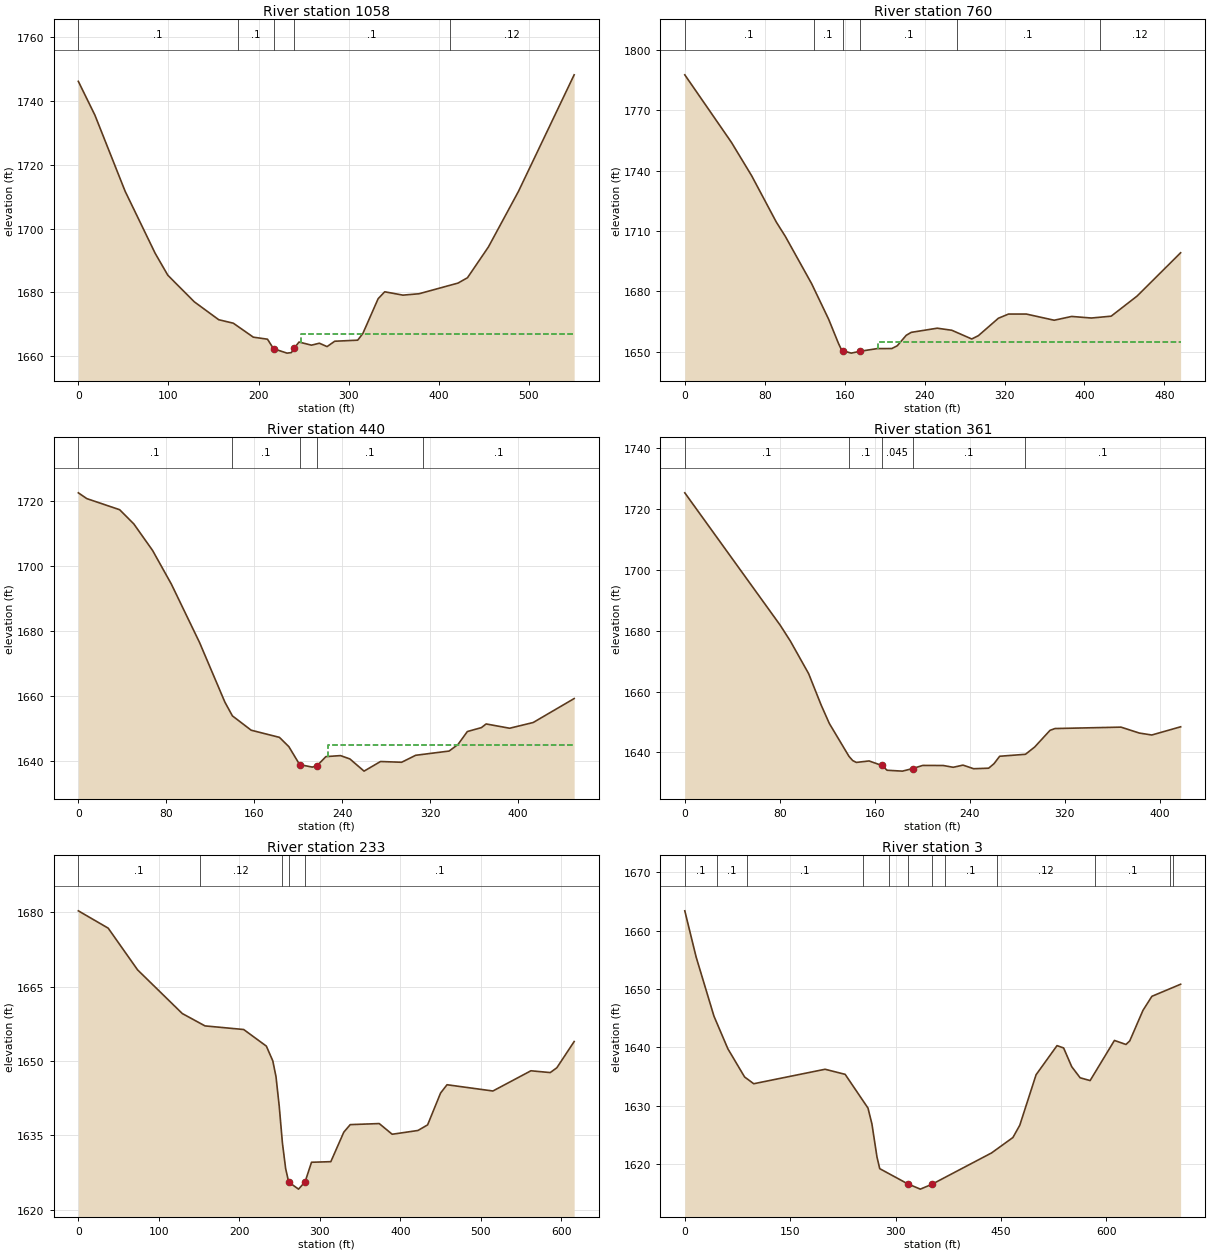
Type RM Length L Ch R = 1 ,1058    ,295.6,298.1,294.7
XS GIS Cut Line= 2
2508575.78182579640639.8657255312508981.86701588641011.061519791
#Sta/Elev= 30
       0 1746.04    18.4 1735.47    51.9 1711.68    85.3 1692.23    99.3 1685.39
   128.7 1677.07   155.8 1671.47     172 1670.38   194.2 1666.01   209.9 1665.38
   216.6  1662.4   231.6 1661.02   236.4 1661.18   239.41662.522   244.9 1664.49
   258.7 1663.51   267.5 1664.12     276 1663.06   284.5 1664.74     310 1665.07
   315.7 1667.15   332.7 1678.05     340 1680.21   360.2 1679.16     378 1679.59
   421.3 1682.93   431.8  1684.6   455.1 1694.25   488.4 1711.62   550.2 1748.08
#Mann= 5 ,-1 , 0
       0      .1       0  177.03      .1       0   216.6    .045       0
   239.4      .1       0  412.21     .12       0
#XS Ineff= 2 , 0
                          247.15         1666.95
Permanent Ineff=
       F       F
Bank Sta=216.6,239.4
XS Rating Curve= 0 ,0
Exp/Cntr=0.3,0.1

Type RM Length L Ch R = 1 ,760     ,323.1,320.1,315.6
XS GIS Cut Line= 2
2508377.46128751640858.5353455832508774.31031666641156.332036973
#Sta/Elev= 30
       0 1787.68    46.6 1754.17    66.9 1737.53    91.6 1714.48   100.6 1707.39
   126.9  1683.9     144 1666.15   153.9 1654.05   156.6 1651.25   158.3 1650.54
   166.6 1649.35   175.5 1650.28   192.6  1651.6   207.2 1651.63   212.6    1653
   221.6 1658.21   226.6 1659.67   252.6 1661.74   267.2 1660.72   287.2 1656.38
   293.8 1658.02   313.8 1666.68     324 1668.78   341.7 1668.78   369.7  1665.7
   387.1 1667.58   406.9  1666.8   426.7 1667.72   452.6  1677.7   496.2 1699.23
#Mann= 6 ,-1 , 0
       0      .1       0  128.81      .1       0   158.3    .045       0
   175.5      .1       0  272.02      .1       0  415.23     .12       0
#XS Ineff= 2 , 0
                          192.98         1654.74
Permanent Ineff=
       F       F
Bank Sta=158.3,175.5
XS Rating Curve= 0 ,0
Exp/Cntr=0.3,0.1

Type RM Length L Ch R = 1 ,440     ,71.5,79.2,71.6
XS GIS Cut Line= 2
2508195.52833559  641175.78298722508617.71151218641335.097393462
#Sta/Elev= 30
       0 1722.53     7.7 1720.75    37.6 1717.33    50.5 1712.95    67.6 1704.77
    84.7 1694.39   110.3 1676.44   133.4 1658.05   140.2 1653.84   157.3 1649.42
     183 1647.22   191.6 1644.35   201.4 1638.83   212.9 1638.06   217.2 1638.48
   225.3 1641.29   238.6  1641.6   247.1 1640.58     260 1636.82     275 1639.78
   294.2 1639.55     307  1641.7   337.4    1643   345.5 1645.03     354 1649.01
   366.8 1650.22   371.1 1651.35   392.5 1650.03   413.9 1651.79   451.2 1659.17
#Mann= 5 ,-1 , 0
       0      .1       0  139.62      .1       0   201.4    .045       0
   217.2      .1       0  313.78      .1       0
#XS Ineff= 2 , 0
                          226.78         1644.89
Permanent Ineff=
       F       F
Bank Sta=201.4,217.2
XS Rating Curve= 0 ,0
Exp/Cntr(USF)=0,0
Exp/Cntr=0.3,0.1

Type RM Length L Ch R = 1 ,361     ,135.4,127.6,124.8
XS GIS Cut Line= 2
2508175.69312708641243.1917490592508565.49383516641393.115098321
#Sta/Elev= 30
       0 1725.17    80.4 1681.72    88.8 1676.62   104.3 1665.86   114.7 1655.69
   121.7 1649.53   138.3 1638.72   141.4 1637.35   144.5 1636.74   155.2 1637.22
     166 1635.73   170.4 1634.16   183.3 1633.88   191.8 1634.72   200.4 1635.75
   217.6 1635.73   226.1 1635.14   234.3 1635.85   243.3 1634.67   255.9 1634.84
   260.4 1636.31   265.2 1638.76   286.9  1639.4   294.7 1641.79   307.6 1647.26
   311.8 1647.85   367.4 1648.31   382.8 1646.37   393.3 1645.73   417.6 1648.42
#Mann= 5 ,-1 , 0
       0      .1       0   138.3      .1       0     166    .045       0
   191.8      .1       0   286.9      .1       0
Bank Sta=166,191.8
XS Rating Curve= 0 ,0
Exp/Cntr(USF)=0,0
Exp/Cntr=0.3,0.1

Type RM Length L Ch R = 1 ,233     ,233.9,230.6,228.3
XS GIS Cut Line= 2
2508001.69580797641382.8917153412508616.38389213641420.065076802
#Sta/Elev= 30
       0 1680.24    37.1 1676.75    73.6 1668.35   129.1 1659.56   157.3 1657.07
   205.4 1656.34   233.5    1653   241.5 1650.04   245.5 1646.85   249.5 1640.91
   253.5 1633.45   257.5 1628.31   261.3 1625.61   273.5  1624.2   281.6 1625.66
   289.6 1629.61   313.6 1629.73   329.7 1635.67   337.7 1637.19   373.7  1637.4
   389.8 1635.25   421.8 1636.01   433.8 1637.14   449.9 1643.55   457.9 1645.22
   514.9 1643.96   562.1 1648.03   586.1 1647.67   594.3 1648.64   615.8 1653.92
#Mann= 5 ,-1 , 0
       0      .1       0  150.57     .12       0  252.36      .1       0
   261.3    .045       0   281.6      .1       0
Bank Sta=261.3,281.6
XS Rating Curve= 0 ,0
Exp/Cntr(USF)=0,0
Exp/Cntr=0.3,0.1

Type RM Length L Ch R = 1 ,3       ,,,
XS GIS Cut Line= 4
2508003.12432715641423.7890510482508217.32624439641630.515669827
2508326.57780886641622.2893392462508580.30050673641465.391353004
#Sta/Elev= 30
       0 1663.41    16.1 1655.51    41.5 1645.36    61.3 1639.77    85.1 1634.94
    98.1 1633.78   199.6 1636.26   228.2 1635.39   260.7 1629.61   266.3 1626.89
   273.5 1621.22   277.4 1619.23   317.3 1616.62   335.2 1615.72   351.7 1616.55
   436.5 1621.92   466.9 1624.56   476.7 1626.67   499.9 1635.32   529.7 1640.31
   539.1 1639.91   550.6 1636.71   562.6  1634.8   576.8 1634.32   611.4  1641.2
   627.8 1640.51   633.2 1641.12     652 1646.35   664.7 1648.76   705.6 1650.83
#Mann= 12 ,-1 , 0
       0      .1       0    45.8      .1       0      88      .1       0
  253.76     .12       0  290.68      .1       0   317.3    .045       0
   351.7      .1       0  370.95      .1       0  443.76     .12       0
  583.13      .1       0  690.64      .1       0  694.33      .1       0
Bank Sta=317.3,351.7
XS Rating Curve= 0 ,0
Exp/Cntr(USF)=0,0
Exp/Cntr=0.3,0.1
LCMann Table=0

Chan Stop Cuts=-1
Use User Specified Reach Order=0
Composite Channel Slope=5